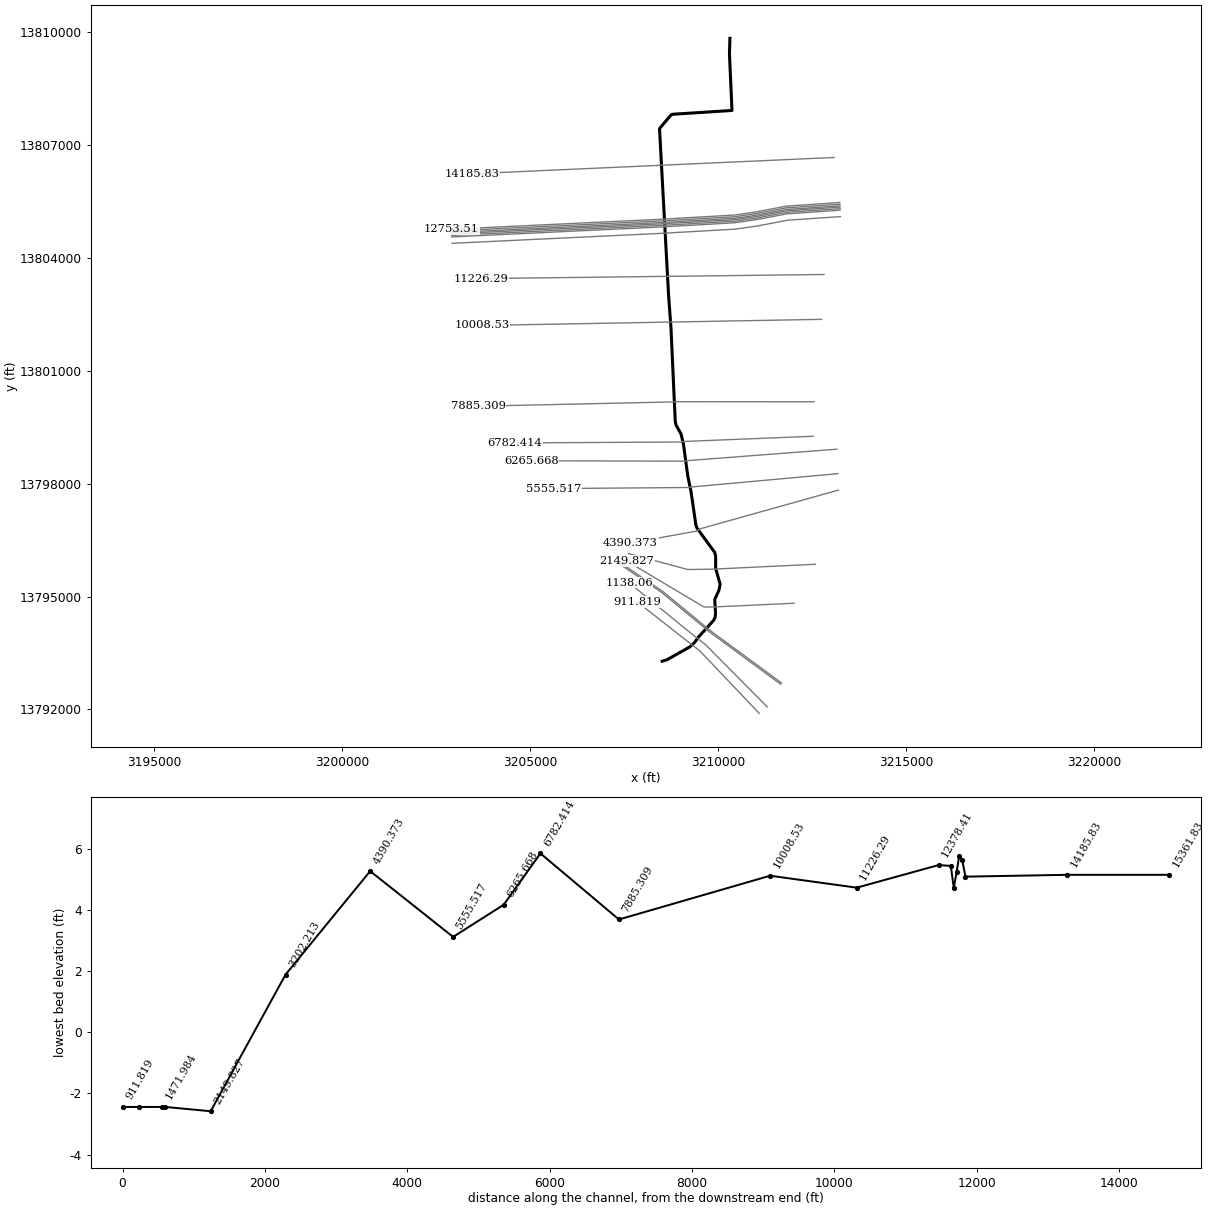
--- B109_00_00.prj (project) ---

Proj Title=B109-00-00
Current Plan=p01
Default Exp/Contr=.3,.1
English Units
Geom File=g01
Geom File=g02
Flow File=f01
Flow File=f02
Plan File=p01
Plan File=p02
Y Axis Title=Elevation
X Axis Title(PF)=Main Channel Distance
X Axis Title(XS)=Station
BEGIN DESCRIPTION:
Armand Bayou
Spring Gully
HCFCD Unit B109-00-00
Flood Hazard Model
10, 2, 1, 0.2% Event
Filename B109_00_00.prj
Prepared by: Christopher Moss Date: 6/15/2004
Reviewd by:		Date:
Status FINAL
END DESCRIPTION:
DSS Export Rating Curves= 0
DSS Export Rating Curve Sorted= 0
DSS Export Volume Flow Curves= 0
DXF OffsetX= 0
DXF OffsetY= 0
DXF ScaleX= 1
DXF ScaleY= 10

--- B109_00_00.p01 (plan) ---

Plan Title=FEMA Effective June 2007
Version=Version 3.0.1  Mar 2001
Short Identifier=FEMAeff0607
Geom File=g01
Flow File=f01
Subcritical Flow
K Sum by GR= 0
Std Step Tol= 0.01
Critical Tol= 0.01
Num of Std Step Trials= 20
Max Error Tol= 0.3
Flow Tol Ratio= 0.001
Split Flow NTrial= 30
Split Flow Tol= 0.02
Split Flow Ratio= 0.02
Log Output Level= 0
Friction Slope Method= 0
Unsteady Friction Slope Method= 2
Secant Critical Depth
Global Vel Dist= 0 , 0 , 0
Global Log Level= 0
CheckData=True
Encroach Param=-1 ,0,0, 0
Computation Interval=1HOUR
Output Interval=1HOUR
Run HTab= 0
Run UNet= 0
Run PostProcess= 0
UNET Theta= 1
UNET ZTol= 0.02
UNET ZSATol= 0.1
UNET MxIter= 20
UNET MaxInSteps= 20
UNET DtIC= 0
UNET DtMin= 0
UNET MaxCRTS= 20
UNET WFStab= 2
UNET SFStab= 1
UNET WFX= 1
UNET SFX= 1
UNET Convert EG Bridges=-1
UNET Use Existing IB Tables=-1
Instantaneous Interval=1HOUR
DSS File=dss
Write IC File= 0
Write Velocity= 0
Write Detailed= 0

--- B109_00_00.p02 (plan) ---

Plan Title=Floodway
Version=Version 3.0.1  Mar 2001
Short Identifier=Floodway0607
Geom File=g02
Flow File=f02
Subcritical Flow
K Sum by GR= 0
Std Step Tol= 0.01
Critical Tol= 0.01
Num of Std Step Trials= 20
Max Error Tol= 0.3
Flow Tol Ratio= 0.001
Split Flow NTrial= 30
Split Flow Tol= 0.02
Split Flow Ratio= 0.02
Log Output Level= 0
Friction Slope Method= 0
Unsteady Friction Slope Method= 2
Secant Critical Depth
Global Vel Dist= 0 , 0 , 0
Global Log Level= 0
CheckData=True
Encroach Param=-1 ,0,0, 2
Encroach River=B109-00-00
Encroach Reach=MAIN
Encroach Node=15361.83
       1 4936.57 5063.43
Encroach Node=14185.83
       1 4936.57 5063.43
Encroach Node=12753.51
       1 4945.44 5054.56
Encroach Node=12708.5
       1 4926.91 5074.95
Encroach Node=12686.5
       1 4926.91 5074.95
Encroach Node=12664.99
       1  4929.4 5077.36
Encroach Node=12630.5
       1  4928.4 5068.78
Encroach Node=12589.5
       1 4932.86 5076.71
Encroach Node=12570.5
       1 4932.86 5076.71
Encroach Node=12548.47
       1 4931.26  5068.2
Encroach Node=12378.41
       1 4936.78 5058.06
Encroach Node=11226.29
       1 4945.67 5054.33
Encroach Node=10008.53
       1 4950.21 5049.79
Encroach Node=7885.309
       1 4940.99 5064.01
Encroach Node=6782.414
       1 4956.41 5045.59
Encroach Node=6265.668
       1  4955.8  5045.2
Encroach Node=5555.517
       1 4957.98 5043.02
Encroach Node=4390.373
       1 4950.09 5047.91
Encroach Node=3202.213
       1 4950.64 5041.36
Encroach Node=2149.827
       1 4958.96 5137.53
Encroach Node=1512.023
       1 4894.07 5092.97
Encroach Node=1471.984
       1 4892.29 5148.31
Encroach Node=1305.022
       1 4892.29 5148.31
Encroach Node=1138.06
       1 4900.32 5084.14
Encroach Node=911.819
       1 4837.58 5058.46
Encroach Reach=B109-00-00_0009
Encroach Node=15361.83
       1 4936.57 5063.43
Encroach Node=14185.83
       1 4936.57 5063.43
Encroach Node=12753.51
       1 4945.44 5054.56
Encroach Node=12708.5
       1 4926.91 5074.95
Encroach Node=12686.5
       1 4926.91 5074.95
Encroach Node=12664.99
       1  4929.4 5077.36
Encroach Node=12630.5
       1  4928.4 5068.78
Encroach Node=12589.5
       1 4932.86 5076.71
Encroach Node=12570.5
       1 4932.86 5076.71
Encroach Node=12548.47
       1 4931.26  5068.2
Encroach Node=12378.41
       1 4936.78 5058.06
Encroach Node=11226.29
       1 4945.67 5054.33
Encroach Node=10008.53
       1 4950.21 5049.79
Encroach Node=7885.309
       1 4940.99 5064.01
Encroach Node=6782.414
       1 4956.41 5045.59
Encroach Node=6265.668
       1  4955.8  5045.2
Encroach Node=5555.517
       1 4957.98 5043.02
Encroach Node=4390.373
       1 4950.09 5047.91
Encroach Node=3202.213
       1 4950.64 5041.36
Encroach Node=2149.827
       1 4958.96 5137.53
Encroach Node=1512.023
       1 4894.07 5092.97
Encroach Node=1471.984
       1 4892.29 5148.31
Encroach Node=1305.022
       1 4892.29 5148.31
Encroach Node=1138.06
       1 4900.32 5084.14
Encroach Node=911.819
       1 4837.58 5058.46
Computation Interval=1HOUR
Output Interval=1HOUR
Run HTab= 0
Run UNet= 0
Run PostProcess= 0
UNET Theta= 1
UNET ZTol= 0.02
UNET ZSATol= 0.1
UNET MxIter= 20
UNET MaxInSteps= 20
UNET DtIC= 0
UNET DtMin= 0
UNET MaxCRTS= 20
UNET WFStab= 2
UNET SFStab= 1
UNET WFX= 1
UNET SFX= 1
UNET Convert EG Bridges=-1
UNET Use Existing IB Tables=-1
Instantaneous Interval=1HOUR
Write IC File= 0
IC Time=0
Write Velocity= 0
Write Detailed= 0

--- B109_00_00.f01 (steady flow) ---

Flow Title=FEMA Effective June 2007
Version=Version 3.0.1  Mar 2001
Number of Profiles= 4
Profile Names=10PCT_10yr, 2PCT_50yr, 1PCT_100yr, 0.2PCT_500yr
River Rch & RM=B109-00-00,B109-00-00_0009            ,15361.83
     748    1082    1253    1757
River Rch & RM=B109-00-00,B109-00-00_0009            ,14185.83
     748    1082    1253    1757
River Rch & RM=B109-00-00,B109-00-00_0009            ,12753.51
     762    1104    1278    1794
River Rch & RM=B109-00-00,B109-00-00_0009            ,12378.41
     806    1172    1359    1914
River Rch & RM=B109-00-00,B109-00-00_0009            ,11226.29
     855    1249    1451    2049
River Rch & RM=B109-00-00,B109-00-00_0009            ,10008.53
     948    1395    1625    2308
River Rch & RM=B109-00-00,B109-00-00_0009            ,7885.309
     989    1459    1701    2420
River Rch & RM=B109-00-00,B109-00-00_0009            ,6782.414
    1009    1490    1739    2475
River Rch & RM=B109-00-00,B109-00-00_0009            ,6265.668
    1037    1534    1791    2552
River Rch & RM=B109-00-00,B109-00-00_0009            ,5555.517
    1085    1609    1880    2683
River Rch & RM=B109-00-00,B109-00-00_0009            ,4390.373
    1136    1689    1976    2825
River Rch & RM=B109-00-00,B109-00-00_0009            ,3202.213
    1183    1763    2064    2956
River Rch & RM=B109-00-00,B109-00-00_0009            ,2149.827
    1214    1813    2124    3043
River Rch & RM=B109-00-00,B109-00-00_0009            ,1512.023
    1240    1855    2174    3118
Boundary for River Rch & Prof#=B109-00-00,B109-00-00_0009            , 1
Up Type= 0
Dn Type= 3
Dn Slope=.0012
DSS Import GetInterval= 0
DSS Import GetPeak= 0
DSS Import FillOption= 0

--- B109_00_00.f02 (steady flow) ---

Flow Title=Floodway
Version=Version 3.0.1  Mar 2001
Number of Profiles= 2
Profile Names=1PCT_100yr, 1PCTFloodway_100yrFW
River Rch & RM=B109-00-00,B109-00-00_0009            ,15361.83
    1253    1253
River Rch & RM=B109-00-00,B109-00-00_0009            ,14185.83
    1253    1253
River Rch & RM=B109-00-00,B109-00-00_0009            ,12753.51
    1278    1278
River Rch & RM=B109-00-00,B109-00-00_0009            ,12378.41
    1359    1359
River Rch & RM=B109-00-00,B109-00-00_0009            ,11226.29
    1451    1451
River Rch & RM=B109-00-00,B109-00-00_0009            ,10008.53
    1625    1625
River Rch & RM=B109-00-00,B109-00-00_0009            ,7885.309
    1701    1701
River Rch & RM=B109-00-00,B109-00-00_0009            ,6782.414
    1739    1739
River Rch & RM=B109-00-00,B109-00-00_0009            ,6265.668
    1791    1791
River Rch & RM=B109-00-00,B109-00-00_0009            ,5555.517
    1880    1880
River Rch & RM=B109-00-00,B109-00-00_0009            ,4390.373
    1976    1976
River Rch & RM=B109-00-00,B109-00-00_0009            ,3202.213
    2064    2064
River Rch & RM=B109-00-00,B109-00-00_0009            ,2149.827
    2124    2124
River Rch & RM=B109-00-00,B109-00-00_0009            ,1512.023
    2174    2174
Boundary for River Rch & Prof#=B109-00-00,B109-00-00_0009            , 1
Up Type= 0
Dn Type= 3
Dn Slope=.0012
DSS Import GetInterval= 0
DSS Import GetPeak= 0
DSS Import FillOption= 0

--- B109_00_00.g01 (geometry) ---

Geom Title=B109-00-00 June 2007
Version=Version 3.0.1  Mar 2001

River Reach=B109-00-00      ,B109-00-00_0009
Reach XY= 30
      3210318.75       13809842.       3210306.5       13809431.
       3210373.5       13807924.       3208791.5       13807823.
      3208741.25       13807793.       3208446.5       13807441.
      3208688.25       13803001.        3208751.       13802156.
       3208865.5       13799649.        3208891.       13799549.
      3209018.75       13799323.      3209082.75       13799054.
      3209197.75       13798210.       3209287.5       13797772.
      3209414.75       13796895.      3209448.25       13796811.
       3209915.5       13796173.      3209939.25       13796068.
      3209939.25       13795751.        3210059.       13795326.
      3210027.25       13795169.      3209915.25       13794924.
        3209937.       13794543.      3209924.25       13794441.
        3209881.       13794361.      3209489.75       13793929.
      3209371.75       13793769.      3209254.75       13793662.
        3208650.       13793321.      3208517.25       13793279.

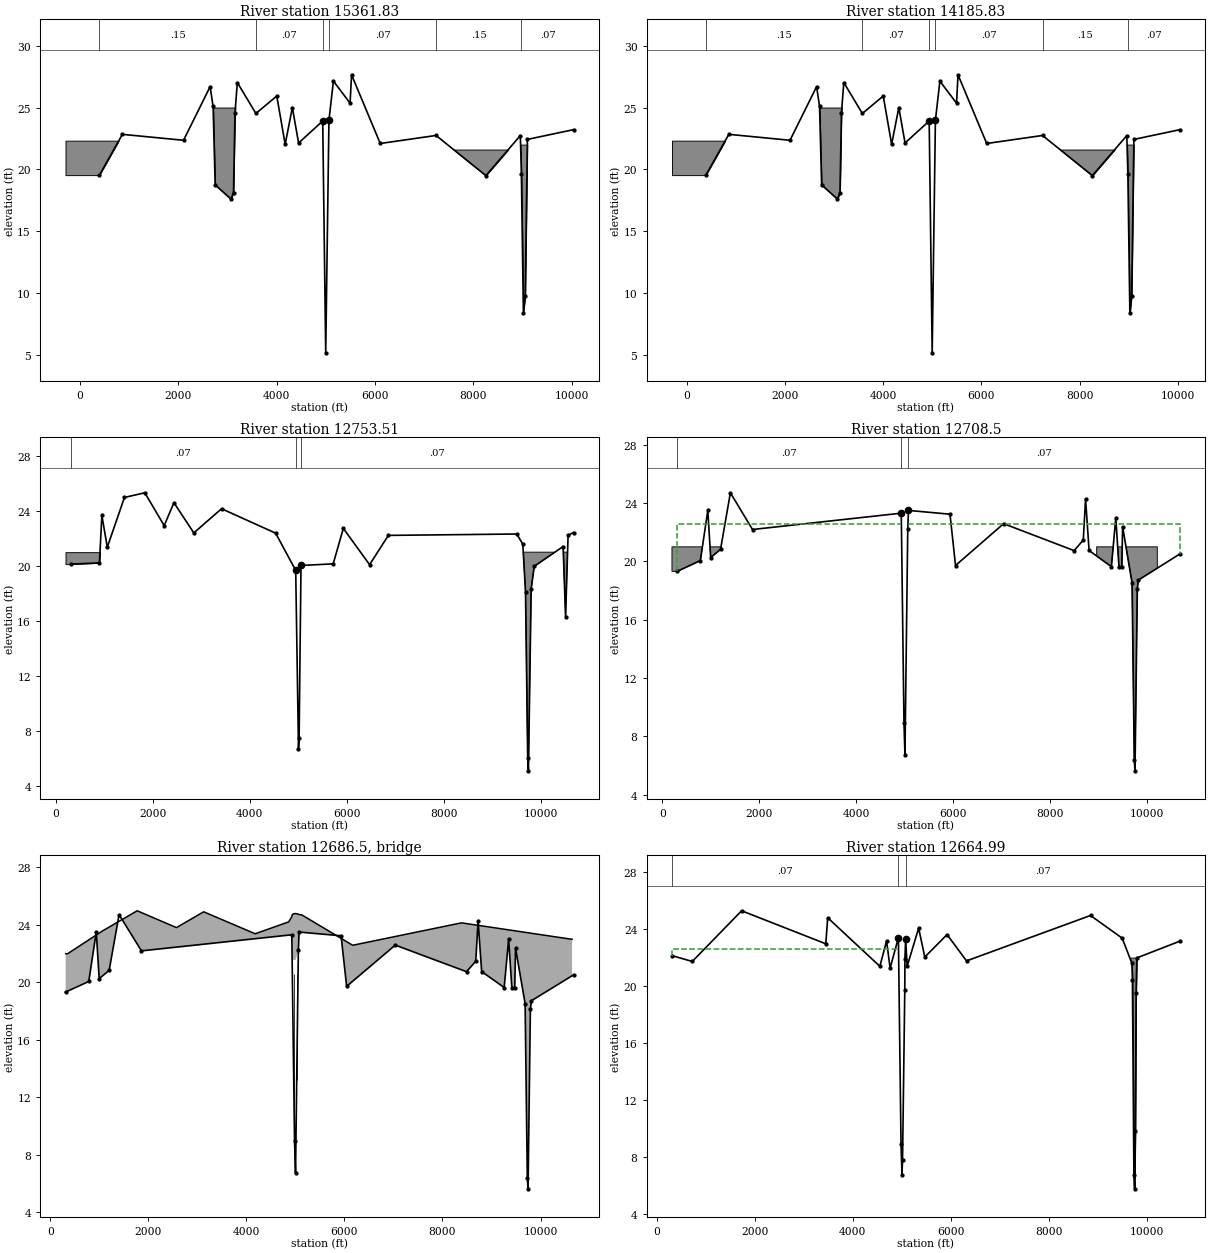
Type RM Length L Ch R = 1 ,15361.83,1430.6,1432.33,1434.02
BEGIN DESCRIPTION:
not a survey cross-section, copied from x/s 14185.83
END DESCRIPTION:
#Sta/Elev= 30
  393.27   19.53  859.68   22.83 2104.83   22.35 2645.61   26.69 2706.12   25.09
  2748.2   18.74 3069.66   17.59 3121.53   18.12 3151.56   24.57 3199.17   27.02
 3576.98   24.52 4002.05   25.93 4172.59   22.02 4318.98      25 4445.66   22.13
 4936.57   23.91 4997.76    5.15 5063.43   23.97 5154.55   27.14 5493.76   25.35
  5523.4   27.65 6107.45   22.09 7243.07   22.74 8256.72   19.49 8957.94   22.73
 8979.64   19.61 9020.43    8.37 9057.79    9.77 9101.73   22.4210040.88   23.21
#Mann= 6 ,-1 , 0
  393.27     .15       0 3576.98     .07       0 4936.57    .032       0
 5063.43     .07       0 7243.07     .15       0 8979.64     .07       0
#Block Obstruct= 4 ,-1
 -297.26  782.27   22.32    2650    3250      25 7588.01 8808.34    21.6
    8900    9160      22
Bank Sta=4936.57,5063.43
XS Rating Curve= 0
Exp/Cntr=.3,.1

Type RM Length L Ch R = 1 ,14185.83,1430.6,1432.33,1434.02
XS GIS Cut Line= 2
     3213091.655    13806674.088     3203453.795    13806240.439
#Sta/Elev= 30
  393.27   19.53  859.68   22.83 2104.83   22.35 2645.61   26.69 2706.12   25.09
  2748.2   18.74 3069.66   17.59 3121.53   18.12 3151.56   24.57 3199.17   27.02
 3576.98   24.52 4002.05   25.93 4172.59   22.02 4318.98      25 4445.66   22.13
 4936.57   23.91 4997.76    5.15 5063.43   23.97 5154.55   27.14 5493.76   25.35
  5523.4   27.65 6107.45   22.09 7243.07   22.74 8256.72   19.49 8957.94   22.73
 8979.64   19.61 9020.43    8.37 9057.79    9.77 9101.73   22.4210040.88   23.21
#Mann= 6 ,-1 , 0
  393.27     .15       0 3576.98     .07       0 4936.57    .032       0
 5063.43     .07       0 7243.07     .15       0 8979.64     .07       0
#Block Obstruct= 4 ,-1
 -297.26  782.27   22.32    2650    3250      25 7588.01 8808.34    21.6
    8900    9160      22
Bank Sta=4936.57,5063.43
XS Rating Curve= 0
Exp/Cntr=.3,.1

Type RM Length L Ch R = 1 ,12753.51,45,45.01,45
XS GIS Cut Line= 6
     3213239.731    13805476.502       3211806.4    13805378.741
     3210994.409    13805223.193     3210430.565    13805142.599
     3208455.524    13805029.955     3202912.196    13804766.478
#Sta/Elev= 30
  311.42   20.13  899.36   20.22  949.86   23.67  1061.2   21.36 1414.96   24.98
 1834.54   25.32 2234.66   22.93 2435.46    24.6 2844.94    22.4  3417.1   24.16
    4532   22.38 4945.44   19.67 5002.76    6.67 5015.92    7.51 5054.56   20.03
 5718.38   20.15 5926.96   22.73  6468.6   20.09 6855.98   22.22 9501.96   22.32
  9627.3   21.58 9682.86   18.09  9727.9       6 9742.92    5.09 9799.54   18.33
 9862.92   19.9710457.96   21.4110508.78   16.31 10560.5   22.2310672.94   22.43
#Mann= 3 ,-1 , 0
  311.42     .07       0 4945.44    .032       0 5054.56     .07       0
#Block Obstruct= 2 ,-1
    9500   11000      21     200    1230      21
Bank Sta=4945.44,5054.56
XS Rating Curve= 0
Exp/Cntr=.5,.3

Type RM Length L Ch R = 1 ,12708.5 ,43.51,43.51,43.51
XS GIS Cut Line= 6
     3213242.215    13805431.571     3211811.918    13805334.052
     3211002.804    13805178.972     3210434.174    13805097.729
     3208457.945    13804985.019     3202914.332    13804721.529
#Sta/Elev= 30
  311.26   19.32  785.66   20.06  938.87   23.51  997.87   20.26 1201.61   20.83
 1403.88   24.71 1860.06   22.19 4926.91   23.31 4982.67    8.93 5002.74    6.73
 5060.61   22.22 5074.95    23.5 5931.69   23.24 6045.22   19.72  7037.2   22.59
 8490.52   20.74 8679.05   21.47 8726.01   24.29 8798.82   20.75 9258.46   19.64
 9349.42      23 9414.88   19.61  9474.1   19.62 9489.96   22.38 9685.18   18.52
 9730.23    6.37 9745.25    5.63 9792.94   18.12  9814.6   18.7210673.12   20.52
#Mann= 3 ,-1 , 0
  311.26     .07       0 4926.91    .032       0 5074.95     .07       0
#XS Ineff= 2 , 0
       0 4926.91    22.6 5074.95       0    22.6
Permanent Ineff=
       F       F
#Block Obstruct= 2 ,-1
     200    1307      21    8955   10205      21
Bank Sta=4926.91,5074.95
XS Rating Curve= 0
Exp/Cntr=.5,.3

Type RM Length L Ch R = 3 ,12686.5 ,,,
BEGIN DESCRIPTION:
West Bound bridge Tim's Bridge
west bound bridge
END DESCRIPTION:
Bridge Culvert--1,0,-1,-1, 0
Deck Dist Width WeirC Skew NumUp NumDn MinLoCord MaxHiCord MaxSubmerge Is_Ogee
2,39,2.6,0, 18, 18, , , .95, 0, 0,0,,
     314     349    1057    1773    2574    3129    4181    4863    4923    4944
    5000    5065    5085    5128    6168    8387   10612   10643
      22   21.98   23.56   24.98   23.81   24.91   23.38   24.21   24.55   24.75
   24.79   24.74   24.71    24.7   22.58   24.14   23.01      23
                                                           21.56   21.56   21.56
   21.56   21.56   21.56   21.56
     314     349    1057    1773    2574    3129    4181    4863    4923    4944
    5000    5065    5085    5128    6168    8387   10612   10643
      22   21.98   23.56   24.98   23.81   24.91   23.38   24.21   24.55   24.75
   24.79   24.74   24.71    24.7   22.58   24.14   23.01      23
                                                           21.56   21.56   21.56
   21.56   21.56   21.56   21.56
Pier Skew, UpSta & Num, DnSta & Num=  ,4973, 4 ,4973, 4 , 3 , 3 , 0 ,,
    1.35    1.35       2       2
       0   19.56   19.56   20.56
    1.35    1.35       2       2
       0   19.56   19.56   20.56
Pier Skew, UpSta & Num, DnSta & Num=  ,5027, 4 ,5027, 4 , 3 , 3 , 0 ,,
    1.35    1.35       2       2
       0   19.56   19.56   20.56
    1.35    1.35       2       2
       0   19.56   19.56   20.56
BR Coef=-1 , 1 , 0 ,, 0 ,,,.8,-1,2,0,
WSPro=,,,, 1 ,,,, 0 ,,,, 0 ,,,,-1 ,-1 ,-1 , 0 , 0 , 0 , 0 , 0
BC Design=,, 0 ,, 0 ,,,,,,
BC HTab HWMax=24.95

Type RM Length L Ch R = 1 ,12664.99,34.48,34.49,34.48
XS GIS Cut Line= 6
     3213244.782    13805388.142      3211817.62    13805290.874
     3211011.479    13805136.276     3210437.904    13805054.362
     3208460.447    13804941.586      3202916.54    13804678.081
#Sta/Elev= 30
   311.1   22.14  725.26   21.73  1731.8   25.29 3448.76   22.97 3487.24    24.8
 4551.26   21.39 4688.06   23.17 4760.24   21.26  4929.4    23.4 4982.67    8.93
 5002.74    6.73 5013.91    7.82 5059.75   19.72 5062.32   21.91 5077.36   23.33
 5107.42   21.38  5342.1   24.07 5467.82   22.04 5922.18   23.62 6318.68   21.77
 8847.62   24.96 9492.36   23.37  9692.1   21.61  9702.6   20.46 9732.64    6.71
 9747.66    5.76 9762.68    9.82 9777.68   19.49  9792.7   21.9810673.32   23.16
#Mann= 3 ,-1 , 0
   311.1     .07       0  4929.4    .032       0 5077.36     .07       0
#XS Ineff= 2 , 0
       0  4929.4    22.6 5077.36       0    22.6
Permanent Ineff=
       F       F
#Block Obstruct= 1 ,-1
    9650    9830      22
Bank Sta=4929.4,5077.36
XS Rating Curve= 0
Exp/Cntr=.5,.3

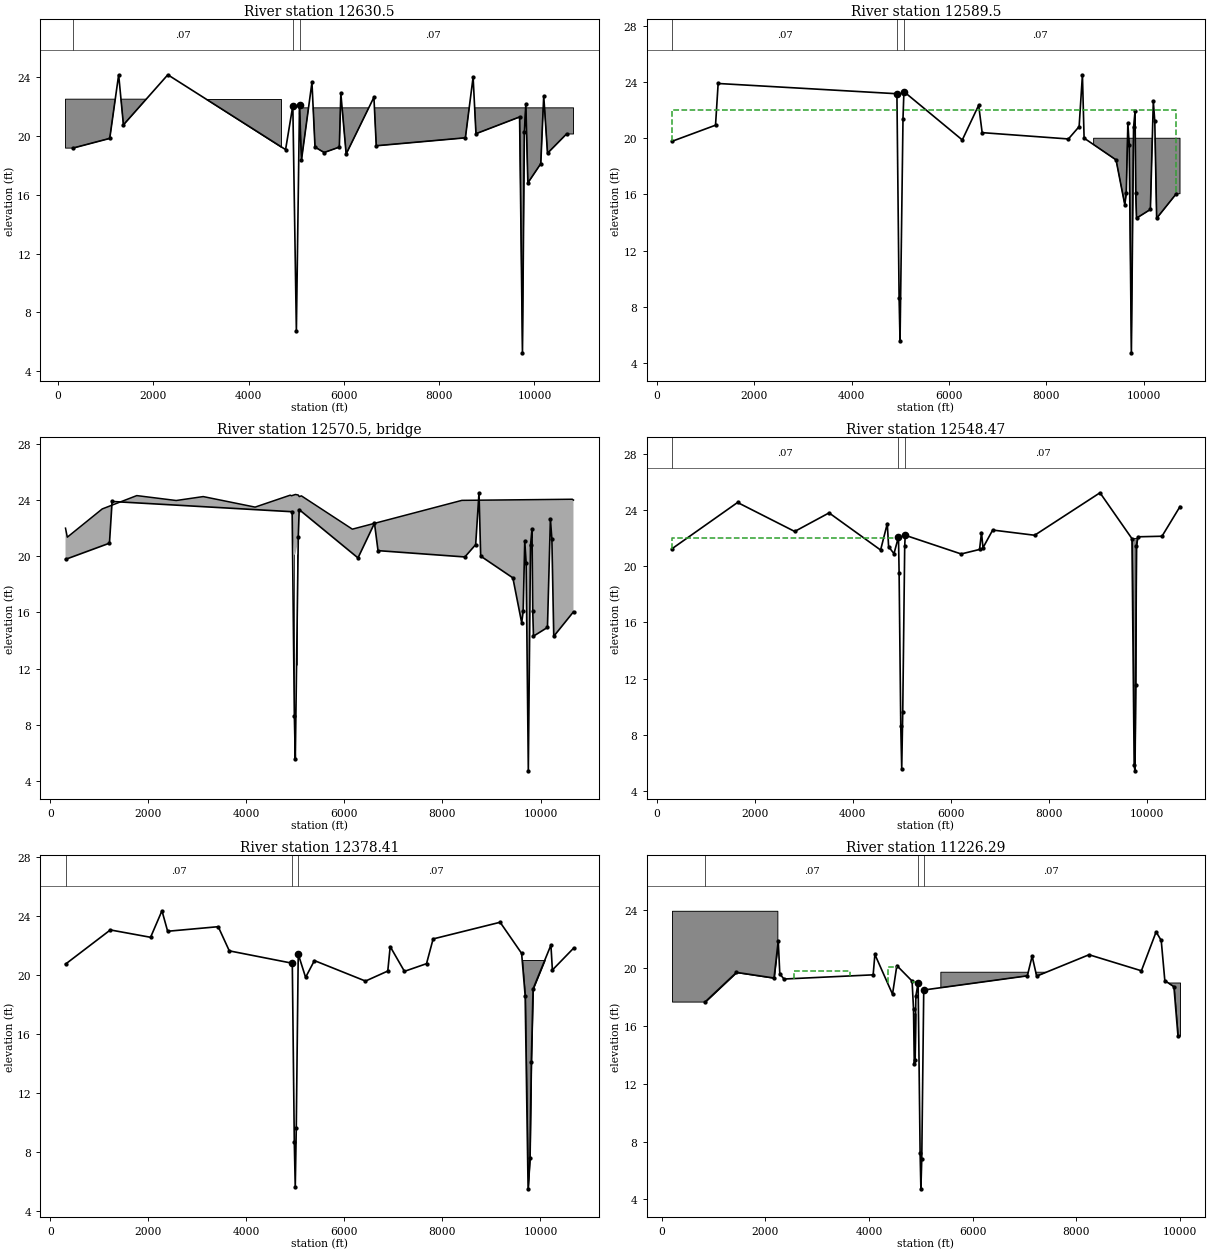
Type RM Length L Ch R = 1 ,12630.5 ,40.99,41,40.99
XS GIS Cut Line= 6
     3213246.189    13805353.681     3211820.747     13805256.55
     3211016.236    13805102.218      3210439.95    13805019.936
     3208461.818    13804907.122     3202917.751     13804643.61
#Sta/Elev= 30
     311   19.18 1085.22   19.84 1272.32   24.17  1372.3   20.76 2304.08   24.17
  4776.4   19.08  4928.4   22.07 5002.74    6.73 5068.78   22.14 5108.74   18.34
 5329.86   23.65 5394.06   19.25 5585.86   18.88 5904.64   19.25 5936.32    22.9
 6047.86   18.78 6630.66   22.64 6679.72   19.34  8550.7   19.88  8712.8   24.01
 8772.88   20.16  9688.9    21.3 9748.98    5.25  9788.8   20.25 9819.56    22.2
 9862.12   16.81 10133.5   18.1210195.38   22.7410274.56   18.8310673.42   20.14
#Mann= 3 ,-1 , 0
     311     .07       0  4928.4    .032       0 5068.78     .07       0
#Block Obstruct= 2 ,-1
  156.45 4677.97   22.51 5065.8810821.21   21.92
Bank Sta=4928.4,5068.78
XS Rating Curve= 0
Exp/Cntr=.5,.3

Type RM Length L Ch R = 1 ,12589.5 ,41.02,41.03,41.02
XS GIS Cut Line= 6
     3213248.286    13805312.739     3211825.406    13805215.813
     3211023.326    13805061.875     3210442.998    13804979.045
     3208463.863    13804866.177     3202919.555    13804602.653
#Sta/Elev= 30
  310.88   19.78 1205.86   20.93 1259.66    23.9 4932.86   23.17 4977.72    8.63
 4997.15    5.57 5058.06    21.4 5076.71   23.32 6276.18   19.88 6612.56   22.35
 6684.56    20.4 8456.74   19.95 8677.02   20.83  8744.8   24.52 8779.04   20.01
 9435.58   18.46  9615.8   15.26 9645.82   16.07 9678.24   21.08  9705.9   19.55
 9750.94    4.72 9795.58   20.77 9826.02   21.93 9841.04   16.07 9856.06   14.31
10141.38   14.9310201.46   22.6310231.48   21.2210269.86    14.310673.58   16.05
#Mann= 3 ,-1 , 0
  310.88     .07       0 4932.86    .032       0 5076.71     .07       0
#XS Ineff= 2 , 0
       0 4932.86      22 5076.71       0      22
Permanent Ineff=
       F       F
#Block Obstruct= 1 ,-1
    8975   10750      20
Bank Sta=4932.86,5076.71
XS Rating Curve= 0
Exp/Cntr=.5,.3

Type RM Length L Ch R = 3 ,12570.5 ,,,
BEGIN DESCRIPTION:
East Bound bridge Tim's Bridge
END DESCRIPTION:
Bridge Culvert--1,0,-1,-1, 0
Deck Dist Width WeirC Skew NumUp NumDn MinLoCord MaxHiCord MaxSubmerge Is_Ogee
2,39,2.6,0, 18, 18, , , .95, 0, 0,0,,
     309     346    1058    1763    2567    3118    4177    4893    4918    4938
    5000    5057    5078    5122    6161    8395   10649   10672
      22   21.36   23.37   24.32   23.97   24.25    23.5   24.35   24.31   24.33
    24.4   24.36   24.25    24.3   21.93   23.98   24.06      24
                                                           20.14   20.14   20.14
   20.14   20.14   20.14   20.14
     309     346    1058    1763    2567    3118    4177    4893    4918    4938
    5000    5057    5078    5122    6161    8395   10649   10672
      22   21.36   23.37   24.32   23.97   24.25    23.5   24.35   24.31   24.33
    24.4   24.36   24.25    24.3   21.93   23.98   24.06      24
                                                           20.14   20.14   20.14
   20.14   20.14   20.14   20.14
Pier Skew, UpSta & Num, DnSta & Num=  ,4973, 4 ,4973, 4 , 3 , 3 , 0 ,,
    1.35    1.35       2       2
       0   18.14   18.14   20.14
    1.35    1.35       2       2
       0   18.14   18.14   20.14
Pier Skew, UpSta & Num, DnSta & Num=  ,5023, 4 ,5023, 4 , 3 , 3 , 0 ,,
    1.35    1.35       2       2
       0   18.14   18.14   20.14
    1.35    1.35       2       2
       0   18.14   18.14   20.14
BR Coef=-1 , 1 , 0 ,, 0 ,,,.8,-1,2,0,
WSPro=,,,, 1 ,,,, 0 ,,,, 0 ,,,,-1 ,-1 ,-1 , 0 , 0 , 0 , 0 , 0
BC Design=,, 0 ,, 0 ,,,,,,
BC HTab HWMax=24.52

Type RM Length L Ch R = 1 ,12548.47,170,170.07,170
XS GIS Cut Line= 6
     3213251.046    13805271.815     3211831.537    13805175.159
     3211032.654     13805021.74     3210447.008    13804938.189
     3208466.553    13804825.248     3202921.929    13804561.709
#Sta/Elev= 30
   310.7   21.23 1648.62   24.52  2813.9   22.46 3515.24   23.78  4566.3   21.14
 4702.68   23.02 4729.76   21.38  4839.2   20.88 4931.26   22.08 4943.68   19.54
 4977.72    8.63 4997.15    5.57 5017.87     9.6 5058.06    21.4  5068.2   22.19
 6209.54   20.86 6584.96   21.18  6624.4   22.38 6654.52    21.3 6852.92   22.56
 7708.56   22.19 9041.52   25.21 9693.46   21.95 9738.52    5.88 9753.52    5.44
 9768.54   11.56 9783.56   21.45 9812.78   22.0810306.12   22.12 10673.8   24.23
#Mann= 3 ,-1 , 0
   310.7     .07       0 4931.26    .032       0  5068.2     .07       0
#XS Ineff= 2 , 0
       0 4931.26      22  5068.2       0      22
Permanent Ineff=
       F       F
#Block Obstruct= 1 ,-1
    9621    9804      22
Bank Sta=4931.26,5068.2
XS Rating Curve= 0
Exp/Cntr=.5,.3

Type RM Length L Ch R = 1 ,12378.41,1157.49,1152.11,1146.06
XS GIS Cut Line= 6
     3213260.429    13805102.074     3211852.383    13805006.335
     3211064.369    13804854.682     3210460.645    13804768.677
     3208475.699    13804655.491        3202930.    13804391.901
#Sta/Elev= 30
   310.1   20.72 1224.82   23.04 2045.62   22.54 2277.96   24.34 2393.72   22.95
 3425.42   23.26 3651.78   21.62 4936.78   20.78 4977.72    8.63 4997.15    5.57
 5017.87     9.6 5058.06    21.4  5208.2   19.82  5387.8   20.96 6430.08   19.57
 6884.74   20.25 6934.02   21.91 7224.46   20.23 7674.98   20.75 7809.92   22.43
 9176.66   23.56 9615.34   21.45 9687.24   18.58 9747.32    5.47  9785.1    7.53
 9813.18   14.07 9848.78   19.0410212.84   22.0110242.88   20.3210674.52    21.8
#Mann= 3 ,-1 , 0
   310.1     .07       0 4936.78    .032       0 5058.06     .07       0
#Block Obstruct= 1 ,-1
    9560   10120      21
Bank Sta=4936.78,5058.06
XS Rating Curve= 0
Exp/Cntr=.3,.1

Type RM Length L Ch R = 1 ,11226.29,1216.78,1217.76,1217.93
XS GIS Cut Line= 2
     3212820.624    13803562.653     3203703.144    13803454.241
#Sta/Elev= 30
  842.14   17.68 1440.36    19.7 2165.32   19.31  2246.7   21.88  2276.7   19.59
 2357.88   19.24 4077.88   19.53  4111.7   20.94 4451.86   18.19 4535.24   20.17
 4829.34    19.1 4856.88   17.18 4871.88   13.38 4886.88   13.64 4901.88   18.05
 4945.67   18.97 4984.35    7.18 4999.26    4.73 5016.15    6.78 5054.33   18.48
 7053.18   19.46 7146.22   20.82 7233.44   19.44 8244.28   20.92 9254.68   19.81
 9538.74    22.5  9637.3   21.91 9707.06   19.13 9882.24   18.71 9960.26   15.32
#Mann= 3 ,-1 , 0
  842.14     .07       0 4945.67    .032       0 5054.33     .07       0
#XS Ineff= 3 ,-1
 2542.37 3624.51   19.81 4355.84 4540.51    20.1 4824.58 4945.09   19.02
Permanent Ineff=
       F       F       F
#Block Obstruct= 4 ,-1
  195.57 2229.47   23.96 4208.57  4926.1   16.86 5384.62 7496.74   19.71
    9625   10000      19
Bank Sta=4945.67,5054.33
XS Rating Curve= 0
Exp/Cntr=.3,.1

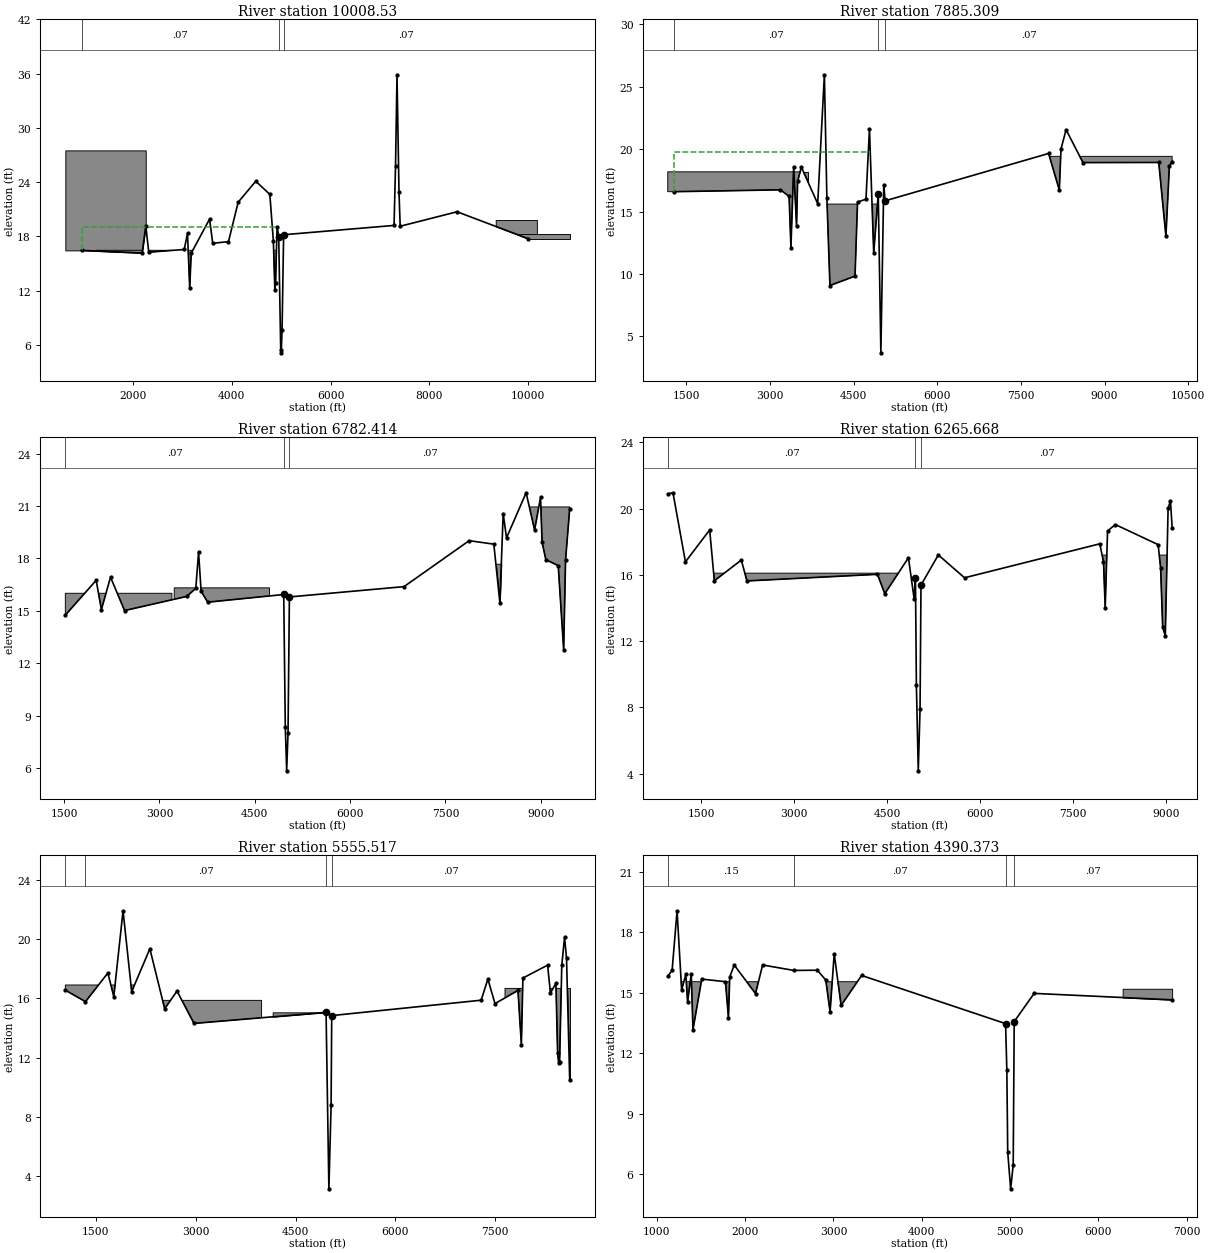
Type RM Length L Ch R = 1 ,10008.53,2123.22,2123.22,2123.22
XS GIS Cut Line= 2
     3212755.577    13802370.117     3203724.826    13802207.499
#Sta/Elev= 30
  967.12   16.45 2182.22   16.16 2256.26   19.17 2316.82   16.25 3035.22   16.55
 3101.88   18.33 3146.88   12.29  3176.9   16.14 3549.28   19.91 3613.12   17.23
 3932.34   17.42    4129   21.78 4485.34    24.1 4770.66   22.64 4842.16   17.46
 4872.16   12.04 4887.18   12.88 4917.18   19.08 4950.21   17.96 4990.75    5.47
 5000.84    5.12 5018.37    7.64 5049.79   18.18 7287.56   19.21 7317.56   25.78
 7347.58   35.87  7387.9   22.87 7412.04   19.12 8564.56   20.72 9999.34   17.76
#Mann= 3 ,-1 , 0
  967.12     .07       0 4950.21    .032       0 5049.79     .07       0
#XS Ineff= 1 ,-1
  848.37 4918.01   19.09
Permanent Ineff=
       F
#Block Obstruct= 4 ,-1
  625.81 2255.54   27.51 1251.12 4909.34   16.46 9348.1110182.53   19.81
 9595.8310847.46   18.22
Bank Sta=4950.21,5049.79
XS Rating Curve= 0
Exp/Cntr=.3,.1

Type RM Length L Ch R = 1 ,7885.309,1064.86,1102.9,1089.95
XS GIS Cut Line= 4
      3212558.99    13800178.561     3208889.789    13800179.655
     3208766.912    13800173.688     3203620.669    13800060.172
#Sta/Elev= 30
 1272.14   16.59 3184.67   16.74 3342.29   16.22 3374.97    12.1 3424.02    18.6
 3475.91   13.83 3494.97   17.41 3561.79   18.56 3854.97   15.63 3974.97   25.95
 4019.97   16.05 4074.59    9.08 4524.24    9.83 4569.67   15.76 4720.71   15.99
 4783.49   21.63 4859.97   11.67 4940.99   16.41 4987.98    3.69 5039.78   17.15
 5064.01   15.86 7995.92   19.65 8188.56   16.72  8218.9   20.02 8309.92   21.55
 8612.69   18.92 9971.86   18.9310100.09   13.0310162.47   18.6510211.86      19
#Mann= 3 ,-1 , 0
 1272.14     .07       0 4940.99    .032       0 5064.01     .07       0
#XS Ineff= 1 ,-1
  844.85 4787.48   19.79
Permanent Ineff=
       F
#Block Obstruct= 3 ,-1
  1166.1 3674.58   18.18 3663.94 4934.55    15.6 7931.7410211.86   19.42
Bank Sta=4940.99,5064.01
XS Rating Curve= 0
Exp/Cntr=.3,.1

Type RM Length L Ch R = 1 ,6782.414,514.16,516.75,521.42
XS GIS Cut Line= 4
     3212529.393    13799261.051     3209097.499    13799122.837
     3209009.433     13799108.77     3204597.373    13799083.468
#Sta/Elev= 30
 1520.07   14.76 2005.52   16.75 2088.04   15.08 2231.17   16.93 2452.41   15.02
 3430.04   15.83 3573.25   16.29 3616.54   18.38 3656.64   16.12 3760.49    15.5
 4956.41   15.94 4981.16    8.37 5002.72    5.85 5024.25    8.02 5045.59    15.8
 6849.08   16.39 7874.34   19.02 8262.35   18.82 8357.07   15.48 8409.42   20.57
  8461.9   19.18 8770.18   21.76 8903.86   19.63 8997.27    21.5 9021.46   18.93
 9080.99   17.93  9275.4   17.59 9361.14   12.78 9390.97   17.91 9456.06   20.86
#Mann= 3 ,-1 , 0
 1520.07     .07       0 4956.41    .032       0 5045.59     .07       0
#Block Obstruct= 4 ,-1
 1520.07 3196.81   16.01 3233.38 4732.73   16.32 8065.98 8555.18    17.7
 8759.95 9456.06   20.95
Bank Sta=4956.41,5045.59
XS Rating Curve= 0
Exp/Cntr=.3,.1

Type RM Length L Ch R = 1 ,6265.668,710.53,710.15,709.57
XS GIS Cut Line= 4
     3213164.666     13798917.85      3209179.24    13798612.734
     3209090.917    13798598.922      3205041.33    13798609.915
#Sta/Elev= 30
  960.43   20.89 1044.56   20.95 1245.45   16.78 1636.46   18.71 1711.73   15.64
 2147.05   16.89 2237.45   15.63 4342.47   16.03 4461.06   14.86 4842.84   17.03
 4934.31   14.56  4955.8   15.83 4970.91    9.33  5001.2    4.17 5029.94     7.9
  5045.2   15.38 5324.93    17.2  5747.2   15.82 7929.51   17.87 7988.94   16.79
 8016.69   14.02 8054.75   18.65 8181.69   19.03 8870.59   17.82 8910.95   16.41
 8943.86   12.85 8986.15   12.31 9031.28   20.01 9069.11   20.47 9096.52   18.85
#Mann= 3 ,-1 , 0
  960.43     .07       0  4955.8    .032       0  5045.2     .07       0
#Block Obstruct= 2 ,-1
 1382.01 4771.84    16.1 7519.91 9096.52   17.19
Bank Sta=4955.8,5045.2
XS Rating Curve= 0
Exp/Cntr=.3,.1

Type RM Length L Ch R = 1 ,5555.517,1121.2,1165.14,1196.65
XS GIS Cut Line= 4
     3213189.699    13798266.989     3209288.422    13797911.452
     3209204.356     13797898.57     3205633.271    13797869.988
#Sta/Elev= 30
 1042.75   16.56  1345.7   15.78 1681.13   17.72 1770.74   16.13 1909.41   21.93
  2039.2   16.46 2312.23   19.36 2534.77    15.3 2719.82    16.5 2975.14   14.31
 4957.98   15.06 5000.28    3.12 5033.53    8.76 5043.02   14.84 7286.75   15.88
 7388.01   17.31 7494.52   15.65 7839.58   16.54 7890.63   12.88 7913.99   17.38
 8284.17   18.25 8327.44   16.37 8409.29   17.02 8434.84   12.29  8450.6   11.65
  8464.6   11.71 8497.41   18.23 8539.01   20.14 8568.77   18.72 8616.44   10.49
#Mann= 4 ,-1 , 0
 1042.75     .15       0  1345.7     .07       0 4957.98    .032       0
 5043.02     .07       0
#Block Obstruct= 4 ,-1
 1042.75 2400.46   16.91 2203.39 3989.57   15.87 4156.23 4950.95   15.06
 7645.05 8616.44   16.68
Bank Sta=4957.98,5043.02
XS Rating Curve= 0
Exp/Cntr=.3,.1

Type RM Length L Ch R = 1 ,4390.373,1219.01,1188.16,1145.4
XS GIS Cut Line= 4
     3213202.215    13797828.909     3209514.394    13796797.145
     3209435.695    13796739.057      3207676.47    13796422.347
#Sta/Elev= 30
 1122.54   15.82 1171.84   16.11 1227.87   19.07 1279.88   15.14 1326.79   15.91
 1347.37   14.55 1388.43   15.93 1408.28   13.17 1507.88   15.68 1776.19   15.55
 1810.19   13.76 1824.56   15.78 1875.25   16.38 2116.93   14.96  2197.3   16.38
 2551.23   16.11 2817.86   16.12 2912.93   15.63 2961.61   14.05 3008.33   16.94
 3086.53   14.37 3318.81   15.86 4950.09   13.47 4964.35   11.16 4974.33    7.08
 5007.72    5.27 5036.48    6.45 5047.91   13.57 5273.62   14.97 6837.29   14.65
#Mann= 4 ,-1 , 0
 1122.54     .15       0 2551.23     .07       0 4950.09    .032       0
 5047.91     .07       0
#Block Obstruct= 2 ,-1
 1015.65 3432.86   15.55 6276.45 6837.29    15.2
Bank Sta=4950.09,5047.91
XS Rating Curve= 0
Exp/Cntr=.3,.1

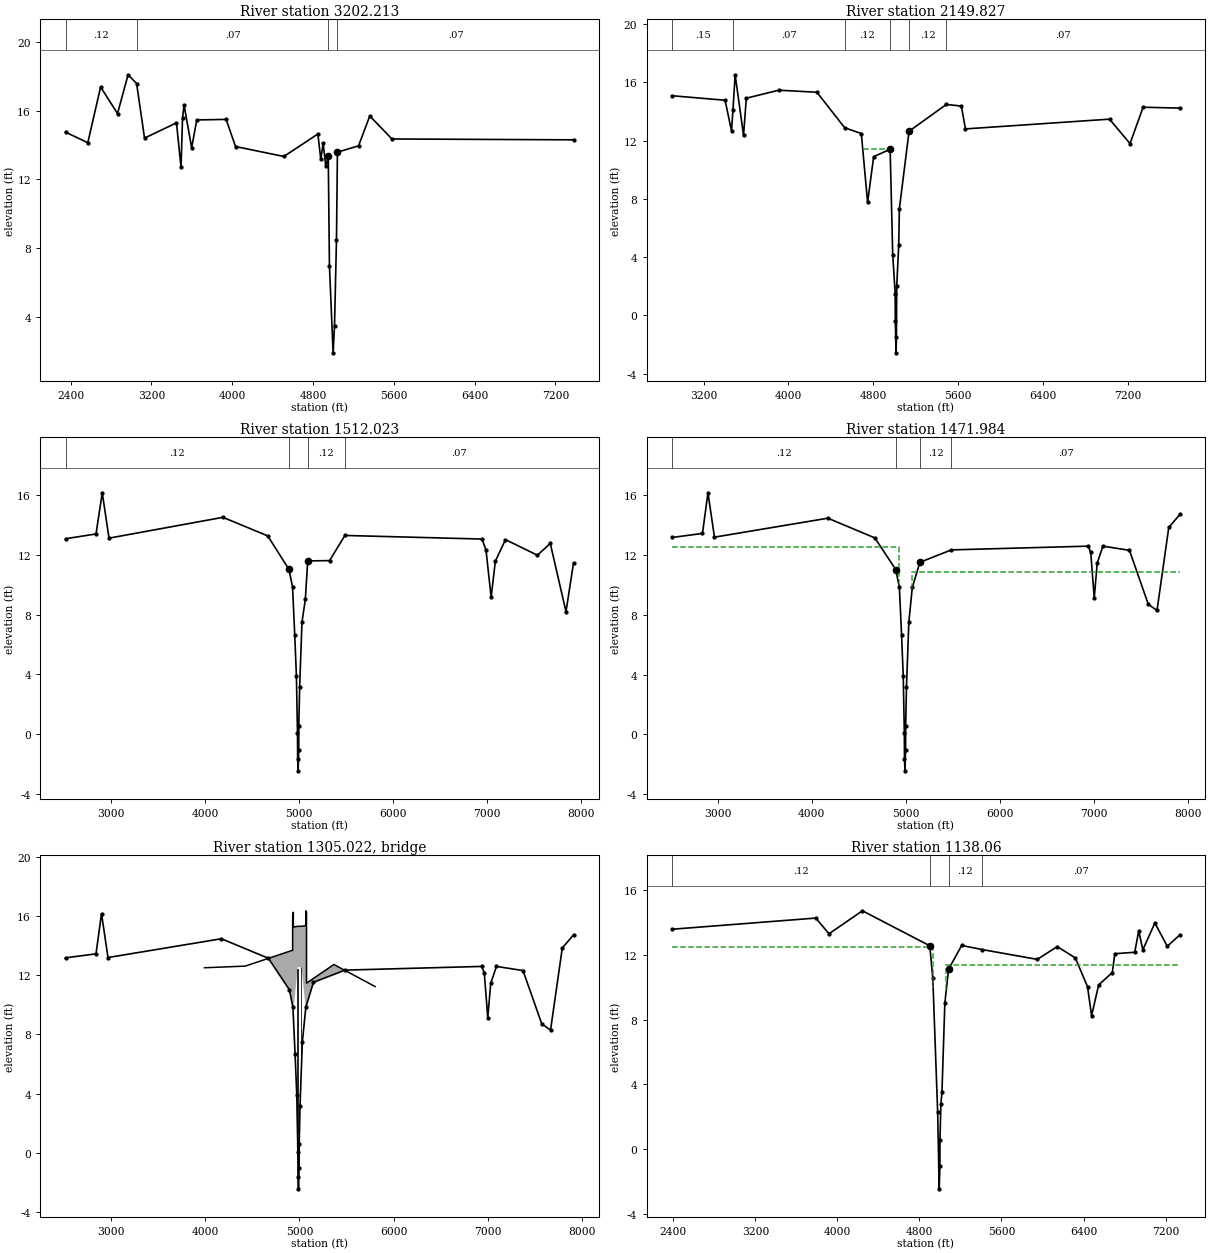
Type RM Length L Ch R = 1 ,3202.213,1015.86,1052.39,1011.86
XS GIS Cut Line= 5
     3212588.587    13795857.386     3209986.883    13795733.545
     3209896.434    13795726.598      3209197.76    13795718.235
     3207617.828    13796142.468
#Sta/Elev= 30
  2349.2   14.75 2569.88   14.13 2696.67   17.38 2864.16   15.83 2968.72   18.09
  3053.4   17.58 3131.52    14.4 3447.87   15.29 3492.92   12.71 3507.94   15.57
 3522.96   16.33 3598.04   13.84 3649.19   15.46 3939.15   15.49 4032.69   13.91
 4510.83   13.33 4847.89   14.64 4876.56   13.17 4900.15   14.09 4926.35   12.75
 4950.64   13.33 4962.28    6.97  4998.7    1.89 5012.54    3.46 5032.03    8.46
 5041.36   13.58  5250.4   13.95 5361.67   15.69 5581.22   14.35 7379.19    14.3
#Mann= 4 ,-1 , 0
  2349.2     .12       0  3053.4     .07       0 4950.64    .032       0
 5041.36     .07       0
Bank Sta=4950.64,5041.36
XS Rating Curve= 0
Exp/Cntr=.3,.1

Type RM Length L Ch R = 1 ,2149.827,731.28,637.8,507.01
XS GIS Cut Line= 5
     3212026.243    13794821.488     3209971.679    13794725.879
     3209884.663    13794722.767     3209628.509    13794721.695
     3207572.515     13795945.22
#Sta/Elev= 30
 2900.88   15.09 3401.84   14.78 3462.66   12.67 3475.98    14.1  3496.9   16.53
 3575.98   12.37 3602.07   14.92 3908.12   15.47 4267.85   15.33 4530.34   12.89
 4687.18   12.49 4746.18    7.76 4803.58    10.9 4958.96   11.41 4983.16    4.17
 5006.52    1.47 5007.77    -.38 5014.77   -2.58 5018.24    -1.5 5021.08    2.01
 5039.93    4.85 5046.04    7.33 5137.53   12.65 5488.85   14.49 5630.44   14.38
 5669.36   12.81 7028.54   13.48 7221.87    11.8 7345.02    14.3 7693.41   14.24
#Mann= 6 ,-1 , 0
 2900.88     .15       0 3475.98     .07       0 4530.34     .12       0
 4958.96    .032       0 5137.53     .12       0 5488.85     .07       0
#XS Ineff= 1 ,-1
 4699.16 4957.62   11.41
Permanent Ineff=
       F
Bank Sta=4958.96,5137.53
XS Rating Curve= 0
Exp/Cntr=.3,.1

Type RM Length L Ch R = 1 ,1512.023,40.14,40.04,40.04
XS GIS Cut Line= 5
     3211691.813    13792700.741      3209744.46    13794131.297
     3209643.729    13794220.992     3208524.933    13795142.008
     3207364.041    13795925.611
#Sta/Elev= 30
 2518.27   13.06  2842.7   13.38 2908.94   16.13 2980.76    13.1  4191.9   14.49
 4668.55   13.25 4894.07   11.01 4932.01    9.83 4955.09    6.65 4972.99    3.91
 4984.45     .08 4986.17   -1.63    4991   -2.44 4997.83   -1.03 4998.56     .56
 5007.57    3.19 5032.26     7.5 5067.99    9.01 5092.97   11.58 5325.66    11.6
 5488.79   13.28 6945.89   13.04 6988.84    12.3 7043.02    9.15    7088   11.56
 7195.55      13 7535.02   11.96 7671.77   12.75 7838.82    8.19 7919.22   11.45
#Mann= 4 ,-1 , 0
 2518.27     .12       0 4894.07    .042       0 5092.97     .12       0
 5488.79     .07       0
#Block Obstruct= 2 , 0
                         6778.16           12.64
Bank Sta=4894.07,5092.97
XS Rating Curve= 0
Exp/Cntr=.5,.3

Type RM Length L Ch R = 1 ,1471.984,331.03,333.92,341.15
XS GIS Cut Line= 5
     3211668.131    13792668.504     3209719.263    13794100.174
     3209617.708    13794190.603     3208500.978    13795109.918
     3207341.662    13795892.457
#Sta/Elev= 30
  2513.6   13.17 2837.84   13.44 2896.18   16.16 2965.17   13.19 4170.32   14.46
    4670   13.14 4892.29   11.02 4930.51    9.83 4953.59    6.65 4971.49    3.91
 4982.95     .08 4984.67   -1.63  4989.5   -2.44 4996.33   -1.03 4997.06     .56
 5006.07    3.19 5030.76     7.5  5067.8    9.83 5148.31   11.51 5483.25   12.34
 6937.23   12.59 6963.98   12.17 7001.38    9.13 7032.83   11.45  7093.6   12.59
 7375.67   12.31 7575.75     8.7 7668.45    8.29 7793.46   13.84 7912.96   14.72
#Mann= 4 ,-1 , 0
  2513.6     .12       0 4892.29    .042       0 5148.31     .12       0
 5483.25     .07       0
#XS Ineff= 2 , 0
       0 4930.51    12.5 5066.64       0   10.84
Permanent Ineff=
       F       F
#Block Obstruct= 2 , 0
                         6914.68           12.27
Bank Sta=4892.29,5148.31
XS Rating Curve= 0
Exp/Cntr=.5,.3

Type RM Length L Ch R = 3 ,1305.022,,,
BEGIN DESCRIPTION:
Red Bluff
END DESCRIPTION:
Bridge Culvert--1,0,-1,-1, 0
Deck Dist Width WeirC Skew NumUp NumDn MinLoCord MaxHiCord MaxSubmerge Is_Ogee
37,81,2.6,0, 17, 17, , , .95, 0, 0,0,,
    3991    4423 4921.34 4927.47 4927.48 4934.87 4934.88 4941.54 4981.57 5021.54
  5058.8 5067.65 5067.66    5075  5075.1    5366    5804
    12.5   12.61   13.67   13.67   15.98   16.25   15.25   15.26    15.3    15.3
   15.34   15.35   16.35   16.21   11.46   12.72   11.23
       0       0       0       0       0       0       0    9.96   12.54   12.53
   10.23       0       0       0       0       0       0
    3991    4423 4921.34 4927.47 4927.48 4934.87 4934.88 4941.54 4981.57 5021.54
  5058.8 5067.65 5067.66    5075  5075.1    5366    5804
    12.5   12.61   13.67   13.67   15.98   16.25   15.25   15.26    15.3    15.3
   15.34   15.35   16.35   16.21   11.46   12.72   11.23
       0       0       0       0       0       0       0    9.96   12.54   12.53
   10.23       0       0       0       0       0       0
Pier Skew, UpSta & Num, DnSta & Num=  ,4979.24, 3 ,4979.24, 3 , 2 , 2 , 0 ,,
     1.3     2.5     2.5
   10.03   10.03   12.54
     1.3     2.5     2.5
   10.03   10.03   12.54
Pier Skew, UpSta & Num, DnSta & Num=  ,5019.15, 3 ,5019.15, 3 , 2 , 2 , 0 ,,
     1.3     2.5     2.5
   10.03   10.03   12.54
     1.3     2.5     2.5
   10.03   10.03   12.54
BR Coef=-1 , 1 , 0 ,, 0 ,,,.8,0,2,0,
WSPro=,,,, 1 ,,,, 0 ,,,, 0 ,,,,-1 ,-1 ,-1 , 0 , 0 , 0 , 0 , 0
BC Design=,, 0 ,, 0 ,,,,,,
BC HTab HWMax=16.16

Type RM Length L Ch R = 1 ,1138.06 ,224.73,226.24,226.97
XS GIS Cut Line= 4
     3211313.107    13792061.837     3209666.224    13793723.491
     3209223.116    13794070.592     3207635.314    13795370.374
#Sta/Elev= 30
 2386.59   13.58 3788.42   14.27  3918.1    13.3 4243.59   14.72 4900.32   12.56
  4930.1   10.58  4977.5     2.3  4992.5   -2.44 4999.33   -1.03 5000.06     .56
 5009.07     2.8  5019.5    3.54  5047.5    9.01 5084.14   11.12 5212.02   12.58
 5408.74   12.33 5948.82   11.72 6143.52   12.51 6320.11   11.81 6439.25   10.03
  6478.5    8.24 6547.27   10.14 6680.98   10.91 6704.96   12.07 6899.53   12.16
  6938.3   13.48 6978.41   12.31 7095.66   13.97 7216.56   12.53 7340.94   13.24
#Mann= 4 ,-1 , 0
 2386.59     .12       0 4900.32    .042       0 5084.14     .12       0
 5408.74     .07       0
#XS Ineff= 2 , 0
       0 4933.51    12.5 5061.99       0   11.36
Permanent Ineff=
       F       F
#Block Obstruct= 2 , 0
                         6136.52           12.33
Bank Sta=4900.32,5084.14
XS Rating Curve= 0
Exp/Cntr=.5,.3

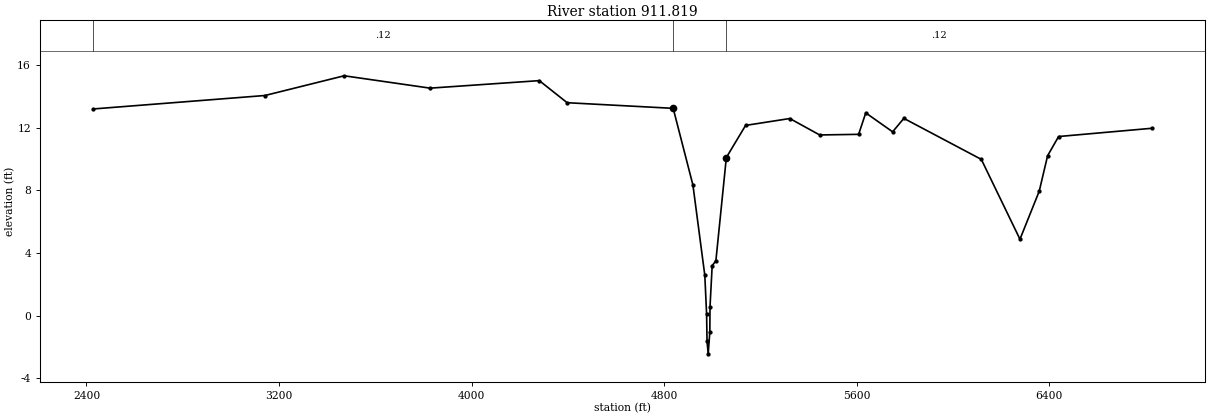
Type RM Length L Ch R = 1 ,911.819 ,915.61,911.82,711.53
XS GIS Cut Line= 4
     3211098.791    13791892.735     3209513.961    13793559.025
     3209073.699    13793899.116     3207859.321    13794854.609
#Sta/Elev= 30
 2427.53    13.2 3141.46   14.06  3470.8   15.32 3827.61   14.53 4281.28   15.01
 4397.12    13.6 4837.58   13.24 4919.61    8.34    4969    2.57 4976.45     .08
 4978.17   -1.63    4983   -2.44 4989.83   -1.03 4990.56     .56 4999.57    3.19
    5015    3.51 5058.46    10.1 5138.41   12.15 5321.98   12.59 5446.19   11.54
 5607.97   11.58 5637.61   12.95  5749.3   11.74 5795.83    12.6 6117.74    9.98
 6278.28    4.88 6358.32    7.95 6393.03   10.21  6438.7   11.44 6828.67   11.97
#Mann= 3 , 0 , 0
 2427.53     .12       0 4837.58    .042       0 5058.46     .12       0
#Block Obstruct= 2 , 0
                         5799.77           12.27
Bank Sta=4837.58,5058.46
XS Rating Curve= 0
Exp/Cntr=.3,.1

Chan Stop Cuts=-1

--- B109_00_00.g02 (geometry) ---

Geom Title= B109-00-00 June 2007 (Floodway)
Version=Version 3.0.1  Mar 2001

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
River Reach=B109-00-00      ,B109-00-00_0009