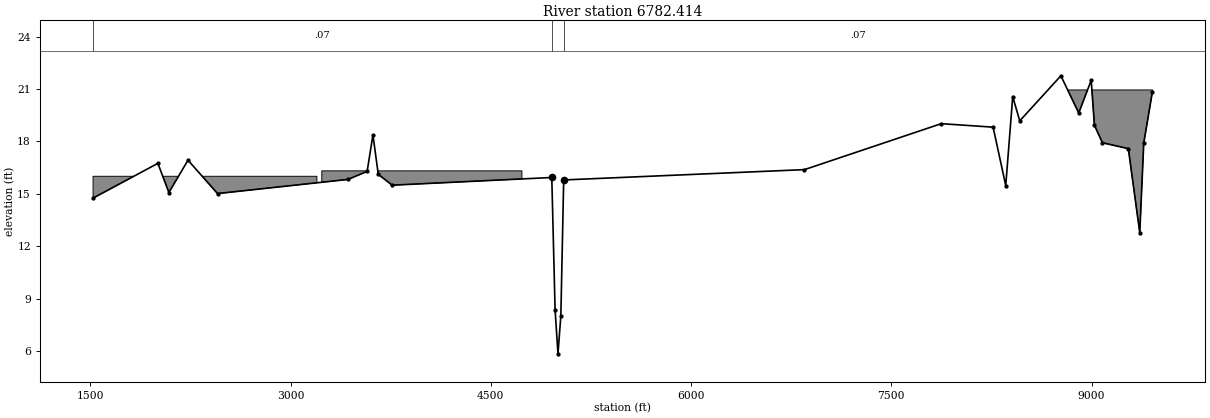
HEC-RAS study B109_00_00.prj: B109-00-00

--- B109_00_00.g02 (geometry) --- (continued)

Type RM Length L Ch R = 1 ,6782.414,514.16,516.75,521.42
XS GIS Cut Line= 4
     3212529.393    13799261.051     3209097.499    13799122.837
     3209009.433     13799108.77     3204597.373    13799083.468
#Sta/Elev= 30
 1520.07   14.76 2005.52   16.75 2088.04   15.08 2231.17   16.93 2452.41   15.02
 3430.04   15.83 3573.25   16.29 3616.54   18.38 3656.64   16.12 3760.49    15.5
 4956.41   15.94 4981.16    8.37 5002.72    5.85 5024.25    8.02 5045.59    15.8
 6849.08   16.39 7874.34   19.02 8262.35   18.82 8357.07   15.48 8409.42   20.57
  8461.9   19.18 8770.18   21.76 8903.86   19.63 8997.27    21.5 9021.46   18.93
 9080.99   17.93  9275.4   17.59 9361.14   12.78 9390.97   17.91 9456.06   20.86
#Mann= 3 ,-1 , 0
 1520.07     .07       0 4956.41    .032       0 5045.59     .07       0
#Block Obstruct= 3 ,-1
 1520.07 3196.81   16.01 3233.38 4732.73   16.32 8759.95 9456.06   20.95
Bank Sta=4956.41,5045.59
XS Rating Curve= 0
Exp/Cntr=.3,.1